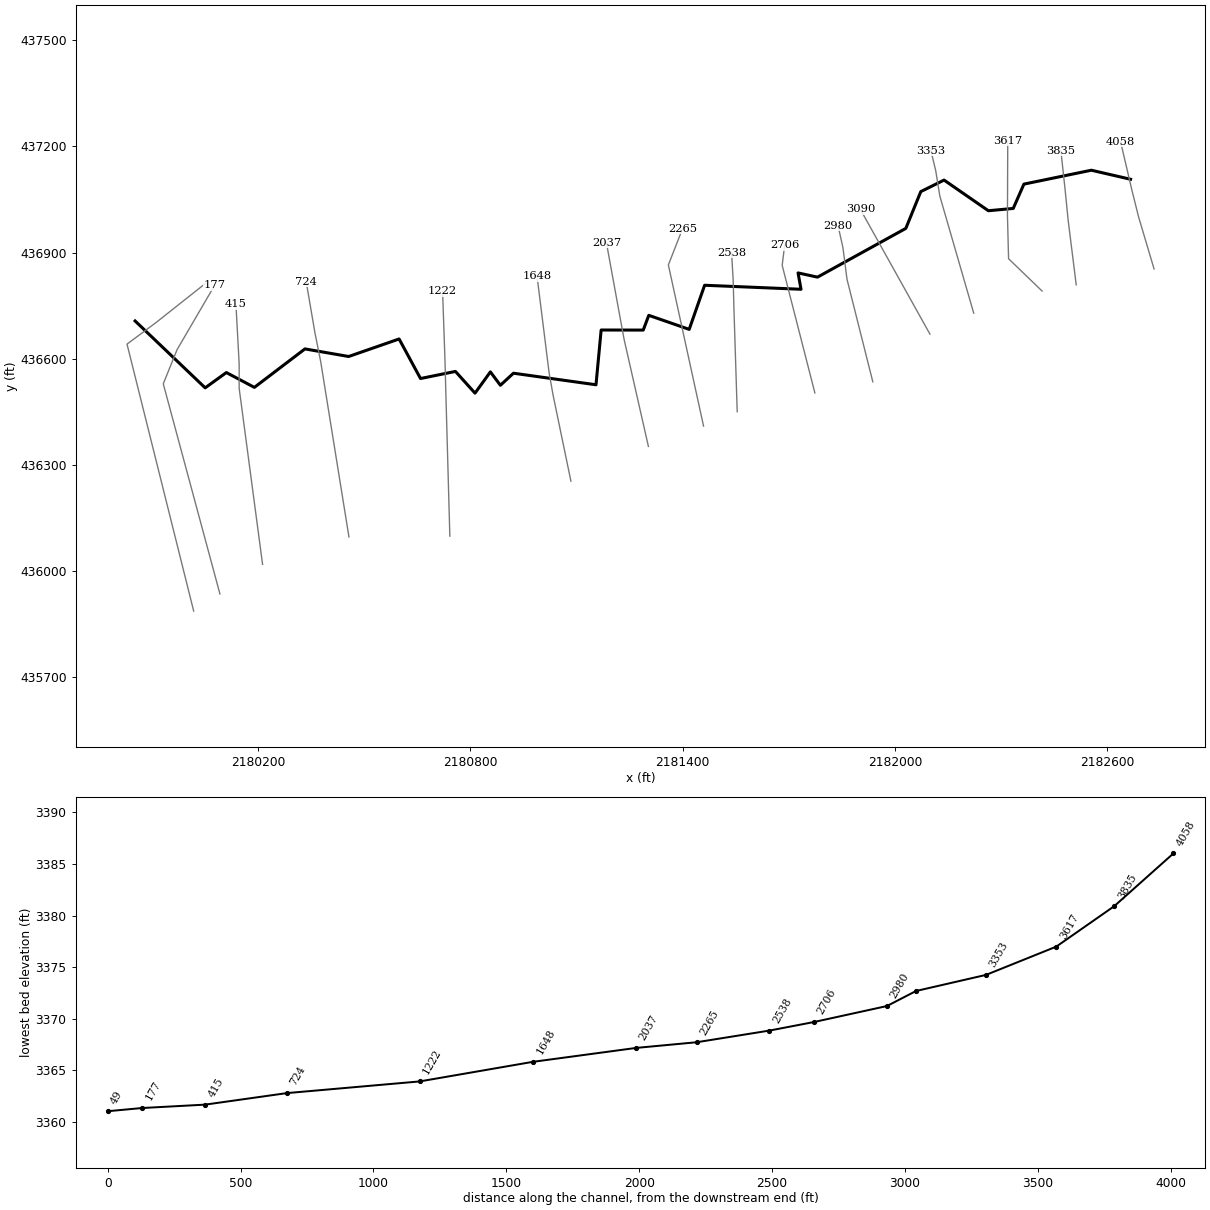
--- CHARLESCKT1.prj (project) ---

Proj Title=CHARLESCKT1
Current Plan=p01
Default Exp/Contr=0,0
English Units
Geom File=g01
Flow File=f01
Plan File=p01
Background Map Layer=Inundation Boundary (01pct Value_0)
Background Map Layer=Inundation Boundary (01pct Value_0)
Background Map Layer=Inundation Boundary (01pct Value_0)
BEGIN DESCRIPTION:
----------MODEL BY WOOD PLC 2021----------
Stream Name: Charles Creek Tributary 1
Flood Zone: Approximate
Pocahontas County, WV
HEC-RAS Version: RAS 6.1
Vertical Datum: NAVD88
Projection: NAD 1983 StatePlane West Virginia S FIPS 4702 (US Feet)
Terrain: 1-meter LIDAR (FEMA Region III 3DEP collected 2016-2018)
Land Use: 2019 NLCD
Hydrologic Method:
WV 2010 Regional Regression Equations
Model Notes:
Model snaps to Charles Creek at the downstream
END DESCRIPTION:
DSS Export Rating Curves= 0
DSS Export Rating Curve Sorted= 0
DSS Export Volume Flow Curves= 0
DXF OffsetX= 0
DXF OffsetY= 0
DXF ScaleX= 0
DXF ScaleY= 0

--- CHARLESCKT1.p01 (plan) ---

Plan Title=Floodplain
Program Version=6.00
Short Identifier=Floodplain
Geom File=g01
Flow File=f01
Subcritical Flow
K Sum by GR= 0
Std Step Tol= 0.01
Critical Tol= 0.01
Num of Std Step Trials= 20
Max Error Tol= 0.3
Flow Tol Ratio= 0.001
Split Flow NTrial= 30
Split Flow Tol= 0.02
Split Flow Ratio= 0.02
Log Output Level= 0
Friction Slope Method= 1
Unsteady Friction Slope Method= 2
Unsteady Bridges Friction Slope Method= 1
Parabolic Critical Depth
Global Vel Dist= 0 , 0 , 0
Global Log Level= 0
CheckData=True
Encroach Param=-1 ,0,0, 0
Mapping Interval=1HOUR
Computation Time Step Use Courant=        0
Computation Time Step Use Time Series=    0
Computation Time Step Count To Double=0
Computation Time Step Max Doubling=0
Computation Time Step Max Halving=0
Computation Time Step Residence Courant=0
Run HTab= 0
Run UNet= 0
Run Sediment= 0
Run PostProcess= 0
Run WQNet= 0
Run RASMapper=-1
UNET Theta= 0
UNET Theta Warmup= 0
UNET ZTol= 0
UNET ZSATol= 0
UNET MxIter= 0
UNET Max Iter WO Improvement= 0
UNET MaxInSteps= 0
UNET DtIC= 0
UNET DtMin= 0
UNET MaxCRTS= 0
UNET WFStab= 0
UNET SFStab= 0
UNET WFX= 1
UNET SFX= 1
UNET Gravity=32.174
UNET 1D Methodology=Finite Difference
UNET DSS MLevel= 1
UNET Pardiso=0
UNET DZMax Abort= 0
UNET Use Existing IB Tables= 0
UNET Froude Reduction=False
UNET Froude Limit= 0
UNET Froude Power= 0
UNET D1 Cores= 0
UNET WindReference=Eulerian
UNET WindDragFormulation=Hsu (1988)
UNET D2 Coriolis=0
UNET D2 Cores= 0
UNET D2 Theta= 1
UNET D2 Theta Warmup= 1
UNET D2 Z Tol= 0.01
UNET D2 Volume Tol= 0.01
UNET D2 Max Iterations= 20
UNET D2 Equation= 0
UNET D2 RampUpFraction=0.1
UNET D2 TimeSlices= 1
UNET D2 Turbulence Formulation=Non-Conservative (original)
UNET D2 Eddy Viscosity=0.3
UNET D2 Transverse Eddy Viscosity=0.1
UNET D2 Smagorinsky Mixing=0
UNET D2 BCVolumeCheck=0
UNET D2 Cores=0
UNET D2 SolverType=PARDISO (Direct)
UNET D2 Minimum Iterations= 2147483647
UNET D2 Maximum Iterations= 2147483647
UNET D2 Restart Number= 10
UNET D2 Relaxation Coeff=1.3
UNET D2 SOR Precondition Iterations= 10
UNET D2 ILUT Maximum Fill= 8
UNET D2 ILUT Tolerance=1E-08
UNET D1D2 MaxIter= 0
UNET D1D2 ZTol=0.01
UNET D1D2 QTol=0.1
UNET D1D2 MinQTol=1
Write IC File= 0
Write IC File at Fixed DateTime=0
Write IC File at Sim End=0
Echo Input=False
Echo Parameters=False
Echo Output=False
Write Detailed= 0
HDF Write Warmup=0
HDF Write Time Slices=0
HDF Flush=0
HDF Compression= 1
HDF Chunk Size= 1
HDF Spatial Parts= 1
HDF Use Max Rows=0
HDF Fixed Rows= 1
Calibration Method= 0
Calibration Iterations= 20
Calibration Max Change=0.05
Calibration Tolerance=0.2
Calibration Maximum=1.5
Calibration Minimum=0.5
Calibration Optimization Method= 1
WQ AD Non Conservative
WQ ULTIMATE=-1
WQ Max Comp Step=1HOUR
WQ Output Interval=15MIN
WQ Output Selected Increments= 0
WQ Output face flow=0
WQ Output face velocity=0
WQ Output face area=0
WQ Output face dispersion=0
WQ Output cell volume=0
WQ Output cell surface area=0
WQ Output cell continuity=0
WQ Output cumulative cell continuity=0
WQ Output face conc=0
WQ Output face dconc_dx=0
WQ Output face courant=0
WQ Output face peclet=0
WQ Output face adv mass=0
WQ Output face disp mass=0
WQ Output cell mass=0
WQ Output cell source sink temp=0
WQ Output nsm pathways=0
WQ Output nsm derived pathways=0
WQ Create Restart=0
WQ Fixed Restart=0
WQ System Summary=0
WQ Write To DSS=0
Sorting and Armoring Iterations= 10
XS Update Threshold= 0.02
Bed Roughness Predictor= 0
Hydraulics Update Threshold= 0.02
Energy Slope Method= 1
Volume Change Method= 1
Sediment Retention Method= 0
Sediment TS Multiplier= 1
Warm Up Method= 0
XS Weighting Method= 0
Number of US Weighted Cross Sections= 1
Number of DS Weighted Cross Sections= 1
Upstream XS Weight=0
Main XS Weight=1
Downstream XS Weight=0
Number of DS XS's Weighted with US Boundary= 1
Upstream Boundary Weight= 1
Weight of XSs Associated with US Boundary= 0
Number of US XS's Weighted with DS Boundary= 1
Downstream Boundary Weight= 0.5
Weight of XSs Associated with DS Boundary= 0.5
Percentile Method= 0
Sediment Output Level= 3
Mass or Volume Output= 0
Output Increment Type= 1
Profile and TS Output Increment= 1
Transport Output Increment 1
XS Output Flag= 0
XS Output Increment= 10
Read HDF5 Sediment Hotstart= 0
Sediment Hotstart Type= 0
Write Gradation File= 0
Read Gradation Hotstart= 0
Write HDF5 File= 1
Write Binary Output= 1
Write DSS Sediment File= 0
DSS Sediment Output Type= 1
SV Curve= 0
Specific Gage Flag= 0
Subcell Erosion Methods= 0
Subcell Deposition Methods= 0
Advection Scheme= 1
Matrix Solver= 0
Implicit Weighting Factor= 1
Maximum Outer Loop Convergence Iterations= 5
Convergence Maximum Absolute= 0.001
Convergence RMSE= 0.0001
Grain Fractions Max Abs Error= 0.001
Max Subgrid Regions= 1
Max Subgrid Length Scale= 3.402823E+38
Initial Layer Thickness= 3.402823E+38
Min Layer Thickness= 3.402823E+38
Max Layer Thickness= 3.402823E+38
Number of Layers= 5

--- CHARLESCKT1.f01 (steady flow) ---

Flow Title=Flow
Program Version=6.10
Number of Profiles= 6
Profile Names=01pct,10pct,04pct,02pct,0_2pct,01plus
River Rch & RM=CHARLESCKT1,Main            ,4058
    98.5    48.6    66.9    82.1     142     146
River Rch & RM=CHARLESCKT1,Main            ,3617
     110    54.7      75    92.1     159     163
River Rch & RM=CHARLESCKT1,Main            ,2265
     124    61.5    84.2     103     178     183
River Rch & RM=CHARLESCKT1,Main            ,1222
     143    71.7    97.8     120     205     212
Boundary for River Rch & Prof#=CHARLESCKT1,Main            , 1
Up Type= 0
Dn Type= 3
Dn Slope=0.014238
Boundary for River Rch & Prof#=CHARLESCKT1,Main            , 2
Up Type= 0
Dn Type= 3
Dn Slope=0.014238
Boundary for River Rch & Prof#=CHARLESCKT1,Main            , 3
Up Type= 0
Dn Type= 3
Dn Slope=0.014238
Boundary for River Rch & Prof#=CHARLESCKT1,Main            , 4
Up Type= 0
Dn Type= 3
Dn Slope=0.014238
Boundary for River Rch & Prof#=CHARLESCKT1,Main            , 5
Up Type= 0
Dn Type= 3
Dn Slope=0.014238
Boundary for River Rch & Prof#=CHARLESCKT1,Main            , 6
Up Type= 0
Dn Type= 3
Dn Slope=0.014238
DSS Import GetInterval= 0
DSS Import GetPeak= 0
DSS Import FillOption= 0

--- CHARLESCKT1.g01 (geometry) ---

Geom Title=Geometry
Program Version=6.10

River Reach=CHARLESCKT1     ,Main
Reach XY= 30
2182666.35494986437107.1540152912182555.45846063437132.733018063
2182364.78574982437093.4909009042182334.61977631 437024.81717324
2182264.34876466 437018.295380682182138.99198583437104.923584427
2182073.21607649437072.299286856     2182030.951      436968.452
      2181781.21      436830.729     2181726.263      436842.667
     2181734.597      436796.486     2181462.097      436807.806
     2181418.478      436683.202      2181304.25      436722.875
     2181288.555      436681.209     2181169.557      436681.411
2181155.00071564436526.711082339      2180921.68      436559.375
     2180884.704      436525.298     2180856.407      436563.127
     2180812.982       436503.04     2180757.622      436564.425
     2180658.871      436544.3782180598.34291142436656.098996892
2180455.73507304436606.580041958     2180332.184      436628.014
      2180189.18      436519.368     2180109.942      436561.247
     2180050.083      436518.049     2179852.005      436706.972

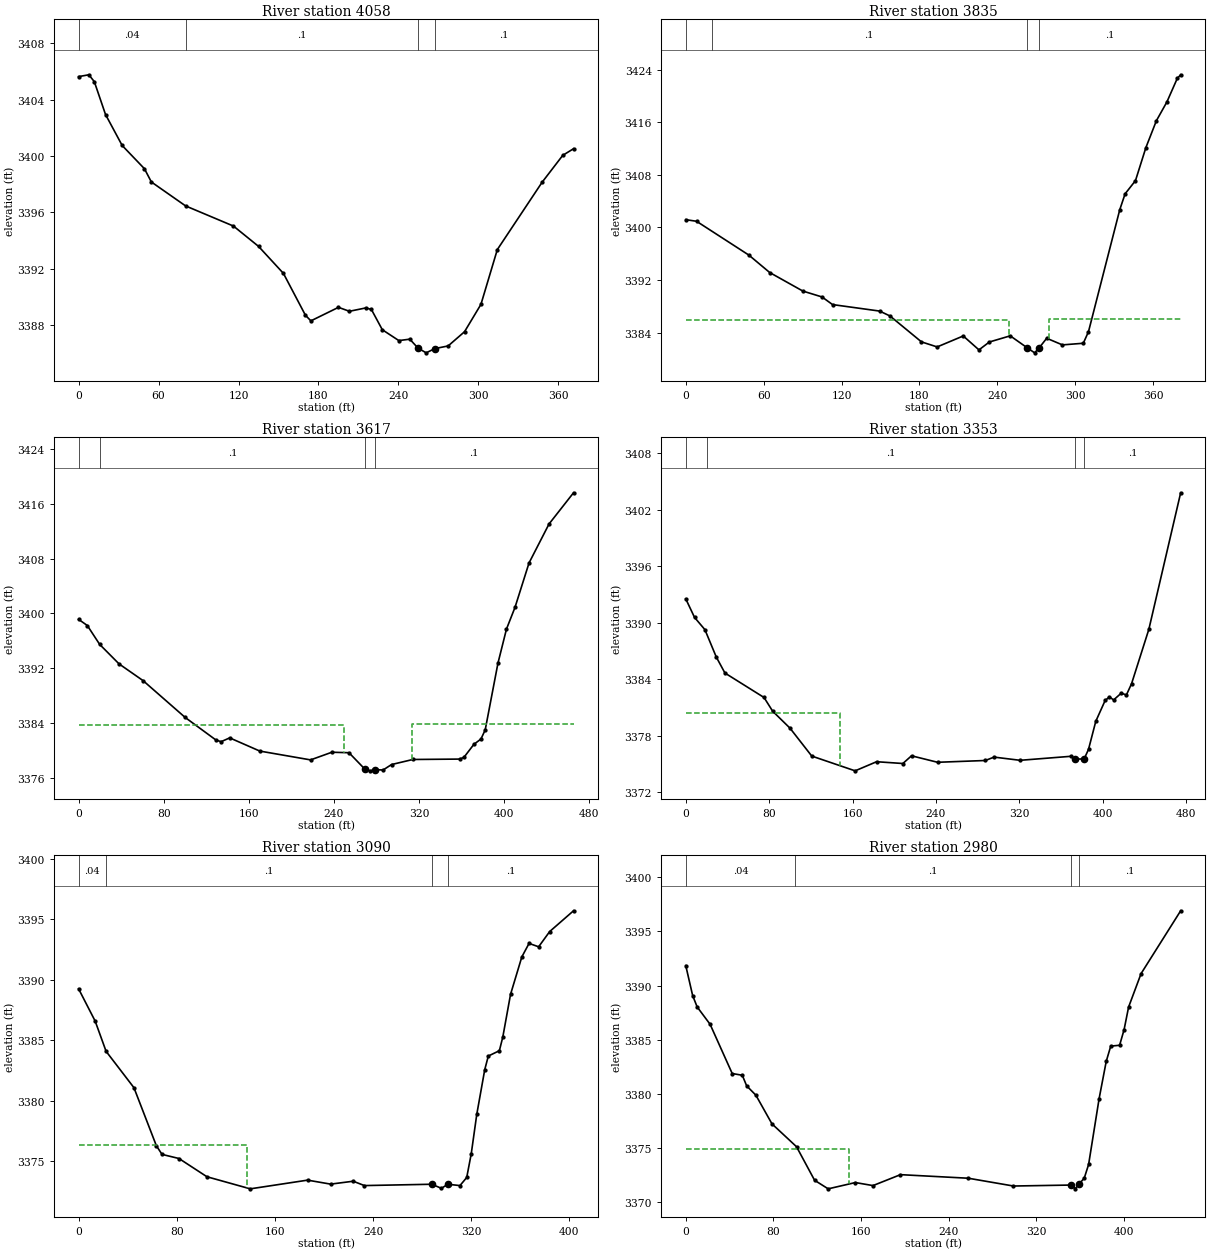
Type RM Length L Ch R = 1 ,4058    ,194,222.9,209.2
XS GIS Cut Line= 4
2182732.74380574436853.821404265 2182689.0838159437000.567481215
2182669.67937597437078.1852409232182638.14716109437212.803542918
#Sta/Elev= 30
       0 3405.64     7.7 3405.77    11.8 3405.28    20.2 3402.95    32.7 3400.75
    49.4  3399.1    54.6 3398.16    80.3 3396.46   116.2 3395.03     135 3393.59
   153.7 3391.67   170.2  3388.7   174.3  3388.3     195 3389.26   203.2 3388.98
   215.6 3389.22   219.7 3389.11   227.9 3387.67   240.3  3386.9   248.5    3387
  254.68 3386.37   260.8 3386.03   267.3 3386.33   277.3 3386.52   289.6 3387.53
   301.9 3389.47   314.2 3393.36   347.8 3398.14   363.3 3400.05371.3718 3400.52
#Mann= 4 ,-1,0
       0     .04       0    80.3      .1       0  254.68    .045       0
   267.3      .1       0
Bank Sta=254.68,267.3
XS Rating Curve= 0 ,0
Exp/Cntr(USF)=0,0
Exp/Cntr=0.3,0.1

Type RM Length L Ch R = 1 ,3835    ,175.6,218,194.6
XS GIS Cut Line= 4
2182512.67641587436808.9548560452182489.85586767436991.519241622
2182480.72764839437082.801434411 2182469.3173743437187.775956119
#Sta/Elev= 30
       0 3401.19     8.3 3400.95    48.6  3395.8    64.7 3393.14    90.2 3390.32
     105 3389.42   113.1 3388.26   149.4 3387.27   157.4 3386.52   181.6 3382.58
   193.7 3381.81   213.8 3383.48   225.9 3381.36   233.9 3382.56     250  3383.5
  262.84 3381.71   268.8 3380.91  272.45 3381.71   278.1 3383.13   290.2 3382.12
   306.3 3382.37   310.3 3384.14   334.4 3402.72   338.5 3405.13   346.5 3407.14
   354.5 3412.16   362.6 3416.26   370.7 3419.12   378.7 3422.71381.3154 3423.26
#Mann= 4 ,-1,0
       0     .04       0      20      .1       0  262.84    .045       0
  272.45      .1       0
#XS Ineff= 2 , 0
          249.36 3385.96  280.12         3386.04
Permanent Ineff=
       F       F
Bank Sta=262.84,272.45
XS Rating Curve= 0 ,0
Exp/Cntr(USF)=0,0
Exp/Cntr=0.3,0.1

Type RM Length L Ch R = 1 ,3617    ,174.2,264.2,210.4
XS GIS Cut Line= 5
2182416.18902201436791.4785565222182321.41408222436882.743313358
2182318.21621259437006.2044314012182318.54743755  437069.3054412
2182319.07396025437216.210694106
#Sta/Elev= 30
       0 3399.14     8.2 3398.24    19.8 3395.48      38 3392.63    60.6 3390.18
   100.2 3384.79   129.3 3381.47     134 3381.26     142 3381.81   170.3 3379.88
     218 3378.59     238 3379.71   254.1 3379.64  269.25  3377.2   274.1 3376.99
   278.1 3377.17   286.1 3377.11   294.1 3377.91   314.1 3378.65   358.1 3378.71
   362.1 3378.96   371.5 3380.87   378.1 3381.64   382.1 3382.97   394.1 3392.74
   402.1 3397.72   410.1 3400.89   423.3 3407.39   442.1 3413.09   465.1 3417.65
#Mann= 4 ,-1,0
       0     .04       0    19.8      .1       0  269.25    .045       0
   278.1      .1       0
#XS Ineff= 2 , 0
           249.3 3383.63  312.96         3383.82
Permanent Ineff=
       F       F
Bank Sta=269.25,278.1
XS Rating Curve= 0 ,0
Exp/Cntr(USF)=0,0
Exp/Cntr=0.3,0.1

Type RM Length L Ch R = 1 ,3353    ,187.9,263.2,247.2
XS GIS Cut Line= 4
2182222.85545377436729.0829373542182127.00915134437059.980886214
2182115.59887724437130.7245856262182101.90654832437187.775956119
#Sta/Elev= 30
       0 3392.54     8.4 3390.57    18.4 3389.26    29.3 3386.35    37.6 3384.65
    75.1 3382.05    83.4 3380.59     100 3378.79   120.9 3375.82   162.5 3374.25
   183.1 3375.22   208.3 3375.03   216.6 3375.85   241.6 3375.16   287.4 3375.35
   295.8 3375.71   320.8 3375.37     370  3375.8   373.23375.505   382.2 3375.51
   386.4 3376.53   393.4 3379.52   402.4 3381.74   406.5 3382.11   410.5 3381.79
   417.7  3382.5   422.8 3382.33   427.7 3383.51   444.3  3389.3 474.829 3403.82
#Mann= 4 ,-1,0
       0     .04       0      20      .1       0   373.2    .045       0
   382.2      .1       0
#XS Ineff= 2 , 0
          148.09 3380.37
Permanent Ineff=
       F       F
Bank Sta=373.2,382.2
XS Rating Curve= 0 ,0
Exp/Cntr(USF)=0,0
Exp/Cntr=0.3,0.1

Type RM Length L Ch R = 1 ,3090    ,137.3,109.7,104
XS GIS Cut Line= 2
2182099.10249506436669.7922140742181902.53224956437021.980570583
#Sta/Elev= 30
       0 3389.24    13.5 3386.57    22.4 3384.07    45.1 3381.06    63.4 3376.25
      68 3375.54    81.8  3375.2   104.6 3373.69   139.9 3372.69   186.6 3373.41
   205.4 3373.08   223.8 3373.32   232.9 3372.96   287.9 3373.07   295.7 3372.73
   300.83373.069   310.8 3372.96   316.3 3373.63     320  3375.6   324.5 3378.86
     331 3382.56   333.9 3383.68   342.9 3384.12   345.7 3385.25     352 3388.78
   361.2 3391.88   367.1    3393   374.9 3392.72   383.9 3393.98403.3318  3395.7
#Mann= 4 ,-1,0
       0     .04       0    22.4      .1       0   287.9    .045       0
   300.8      .1       0
#XS Ineff= 2 , 0
          137.48 3376.29
Permanent Ineff=
       F       F
Bank Sta=287.9,300.8
XS Rating Curve= 0 ,0
Exp/Cntr(USF)=0,0
Exp/Cntr=0.3,0.1

Type RM Length L Ch R = 1 ,2980    ,168.7,274.4,176.8
XS GIS Cut Line= 4
 2181937.5986013436535.1082776782181864.57284707436824.929239783
2181853.16257297436913.9293777522181839.47024405436975.544857884
#Sta/Elev= 30
       0 3391.85     6.3 3389.08    10.4 3388.03    22.2 3386.43    42.4 3381.88
    51.6 3381.72    55.6 3380.74      64 3379.88    78.7 3377.23   101.1 3375.12
   117.6 3372.02     130 3371.23   154.8 3371.81   170.9 3371.53     196 3372.54
   257.9 3372.21   299.1 3371.49   351.6 3371.58   355.6 3371.24   358.8 3371.66
   363.7 3372.21   367.7 3373.48   377.3 3379.57   383.8 3383.01   387.9 3384.41
     396 3384.49   400.1 3385.94   404.2 3388.02   415.6 3391.11451.7266 3396.91
#Mann= 4 ,-1,0
       0     .04       0     100      .1       0   351.6    .045       0
   358.8      .1       0
#XS Ineff= 2 , 0
          148.83 3374.94
Permanent Ineff=
       F       F
Bank Sta=351.6,358.8
XS Rating Curve= 0 ,0
Exp/Cntr(USF)=0,0
Exp/Cntr=0.3,0.1

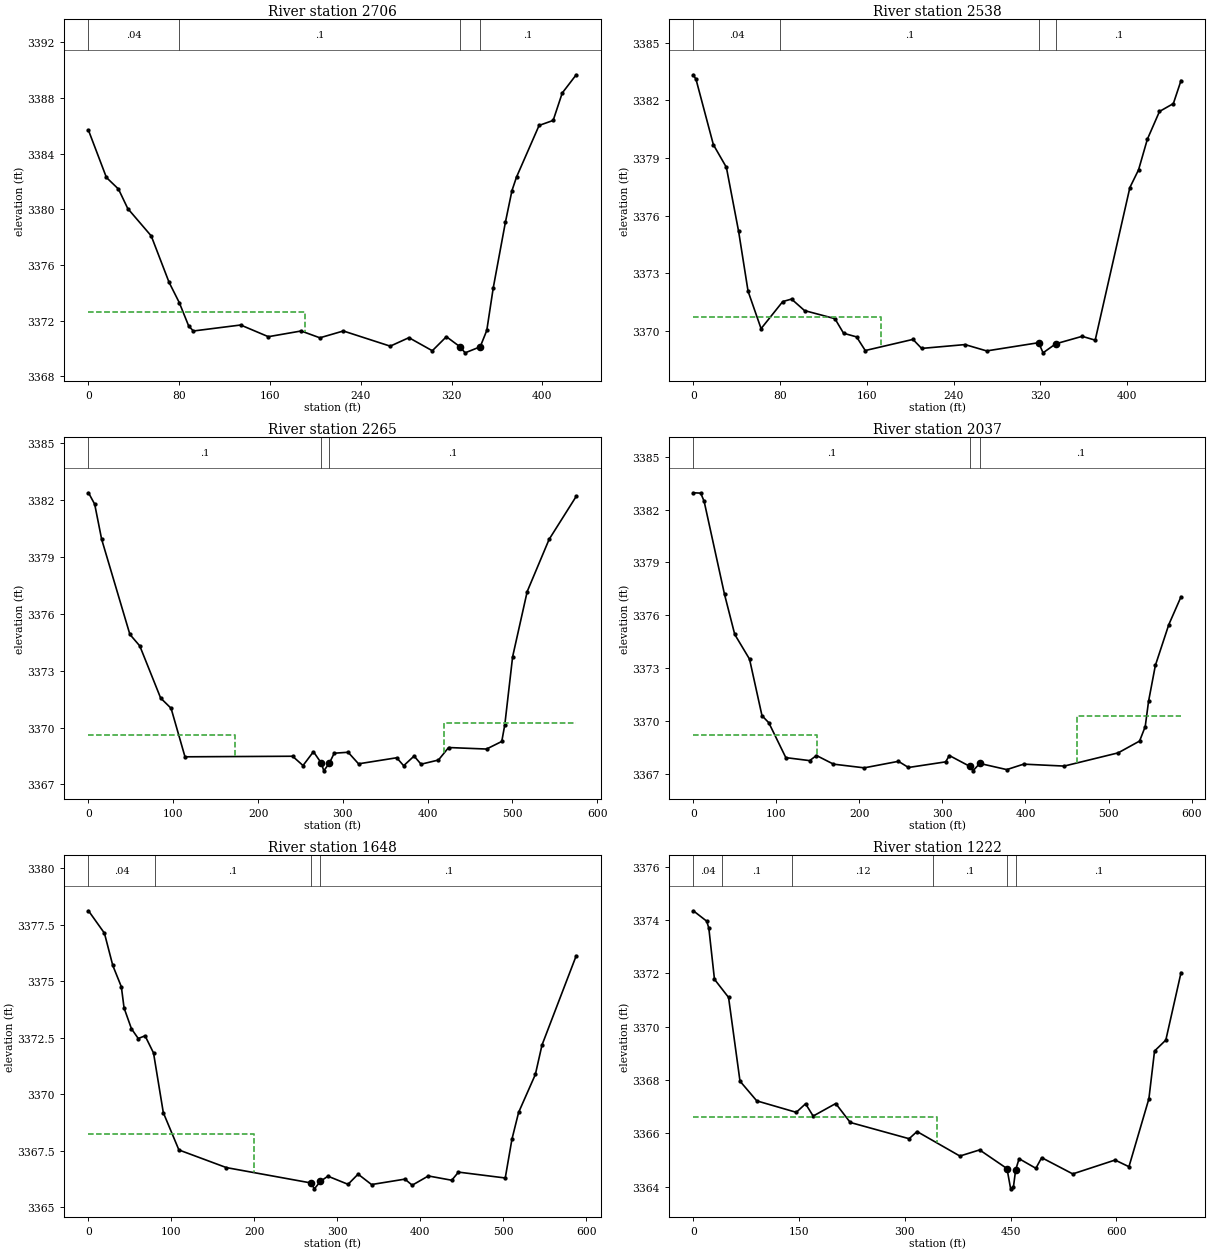
Type RM Length L Ch R = 1 ,2706    ,179.1,167.8,146.8
XS GIS Cut Line= 3
 2181773.8255412436503.6435541922181681.39072338436864.022337597
2181688.41108929436921.355325866
#Sta/Elev= 30
       0 3385.67    15.8 3382.28    26.4 3381.45    34.6 3380.05    55.3 3378.08
      71 3374.75      80 3373.29    88.3 3371.61    92.4 3371.25   134.1 3371.68
   158.5 3370.84   187.4 3371.25   203.9 3370.76   224.6 3371.25   265.9 3370.16
   282.4 3370.77     303 3369.83   315.4 3370.84   327.5 3370.11   331.9 3369.68
   345.23370.114     351 3371.29   356.7 3374.35   367.4 3379.06   373.2 3381.34
   377.2 3382.31   397.1 3386.02   409.5 3386.38   417.5 3388.35429.8056 3389.66
#Mann= 4 ,-1,0
       0     .04       0      80      .1       0   327.5    .045       0
   345.2      .1       0
#XS Ineff= 2 , 0
          190.62 3372.59
Permanent Ineff=
       F       F
Bank Sta=327.5,345.2
XS Rating Curve= 0 ,0
Exp/Cntr(USF)=0,0
Exp/Cntr=0.3,0.1

Type RM Length L Ch R = 1 ,2538    ,143.4,273.5,172
XS GIS Cut Line= 4
2181554.21339159436450.6722493482181545.08517231436738.211156633
2181542.80311749436822.6471849632181538.23900785436900.237048834
#Sta/Elev= 30
       0 3383.33     2.5 3383.09    18.5 3379.69    30.5 3378.51    41.8 3375.17
    50.5 3372.06    62.5 3370.11    82.5 3371.52    90.6 3371.65   102.6 3371.05
   130.6 3370.63   138.6 3369.87   150.6 3369.68   158.6 3368.97   202.6 3369.55
   210.6 3369.08   250.6 3369.28   270.6 3368.95   318.7 3369.38   318.7 3369.36
   322.6 3368.85   334.3 3369.32   358.7 3369.71   370.7 3369.51   402.7 3377.46
   410.7 3378.38   418.8 3379.97     430 3381.42   442.8 3381.83449.8746 3383.03
#Mann= 4 ,-1,0
       0     .04       0      80      .1       0   318.7    .045       0
   334.3      .1       0
#XS Ineff= 2 , 0
          173.02 3370.71
Permanent Ineff=
       F       F
Bank Sta=318.7,334.3
XS Rating Curve= 0 ,0
Exp/Cntr(USF)=0,0
Exp/Cntr=0.3,0.1

Type RM Length L Ch R = 1 ,2265    ,168.3,227.5,164.5
XS GIS Cut Line= 3
2181459.07913622436410.0386753862181359.62395249436865.192398582
2181399.40602598436966.987704284
#Sta/Elev= 30
       0 3382.39     7.3 3381.79    15.5 3379.94    48.8 3374.92    60.5 3374.31
    85.1 3371.56    97.4 3371.02   113.8 3368.46   240.7 3368.49     253    3368
   265.3 3368.73   274.73368.119   277.5 3367.72     284 3368.12   289.8 3368.65
   306.2  3368.7   318.5 3368.09   363.5 3368.41   371.7 3367.99     384  3368.5
   392.2 3368.07   412.7 3368.29   424.7 3368.95   469.4 3368.87   487.4 3369.27
     491 3370.16   500.2 3373.74   517.4 3377.18   543.2 3379.93575.1857  3382.2
#Mann= 3 ,0,0
       0      .1       0   274.7    .045       0     284      .1       0
#XS Ineff= 2 , 0
          172.63 3369.59  419.65         3370.24
Permanent Ineff=
       F       F
Bank Sta=274.7,284
XS Rating Curve= 0 ,0
Exp/Cntr(USF)=0,0
Exp/Cntr=0.3,0.1

Type RM Length L Ch R = 1 ,2037    ,232,388.7,218.4
XS GIS Cut Line= 4
2181303.18736142  436352.54389212181234.72571683436653.775128304
2181223.31544273436715.3906084362181184.52051079 436927.62170667
#Sta/Elev= 30
       0 3382.95     8.9 3382.93      13 3382.47    37.6 3377.18    49.9 3374.91
    67.7 3373.51    82.7  3370.3    90.9  3369.9   111.4 3367.92   140.1 3367.75
   148.3 3368.04   168.8 3367.55   205.8 3367.34     247 3367.71   259.1 3367.36
   303.9 3367.68   308.3 3368.04   332.7 3367.43   336.8 3367.17   344.9 3367.59
   377.5 3367.24   397.8 3367.55   446.6 3367.44   511.6 3368.19   537.4 3368.86
   544.2 3369.68   548.2 3371.11   556.4 3373.15   572.6 3375.47587.3239 3377.05
#Mann= 3 ,-1,0
       0      .1       0   332.7    .045       0   344.9      .1       0
#XS Ineff= 2 , 0
          148.51 3369.19  461.75          3370.3
Permanent Ineff=
       F       F
Bank Sta=332.7,344.9
XS Rating Curve= 0 ,0
Exp/Cntr(USF)=0,0
Exp/Cntr=0.3,0.1

Type RM Length L Ch R = 1 ,1648    ,304.2,426.1,282
XS GIS Cut Line= 4
2181084.11009872436254.4155348522181033.90489269436496.313345743
2181022.49461859436560.210880695 2180988.2637963436834.057459062
#Sta/Elev= 30
       0 3378.12    19.2 3377.13    29.3  3375.7    39.6 3374.76    42.9 3373.82
    51.8  3372.9      60 3372.47    68.2 3372.59    78.4 3371.83    90.2 3369.19
     109 3367.54   166.2 3366.76   268.2 3366.08   272.3 3365.82   279.6 3366.15
   288.6 3366.38   312.9 3366.02     325 3366.47   341.2 3366.01   381.5 3366.25
   390.2 3365.98   409.7 3366.39   437.9  3366.2     446 3366.56   502.4  3366.3
   510.5 3368.02   518.5  3369.2   538.7 3370.88   546.7 3372.18587.9389 3376.13
#Mann= 4 ,-1,0
       0     .04       0      80      .1       0   268.2    .045       0
   279.6      .1       0
#XS Ineff= 2 , 0
             200 3368.26
Permanent Ineff=
       F       F
Bank Sta=268.2,279.6
XS Rating Curve= 0 ,0
Exp/Cntr(USF)=0,0
Exp/Cntr=0.3,0.1

Type RM Length L Ch R = 1 ,1222    ,339.9,498.8,364
XS GIS Cut Line= 4
2180741.80187577436099.2358071112180730.39160167436507.723619841
2180728.10954685436594.4417029912180721.26338239436790.698417487
#Sta/Elev= 30
       0 3374.35      19 3373.96      22  3373.7      30 3371.78      50  3371.1
    66.2 3367.96      90 3367.22     146 3366.79   159.2 3367.11     170 3366.65
     202 3367.12   222.6 3366.41   306.1  3365.8   317.3 3366.07   378.1 3365.15
   406.1 3365.38   444.9 3364.68   450.1 3363.92   454.1    3364   457.2 3364.63
   462.1 3365.05   485.9 3364.69   494.1 3365.09   538.2 3364.48   598.2    3365
   617.9 3364.75   646.2  3367.3   654.2 3369.09   670.2  3369.5691.7714 3372.03
#Mann= 6 ,-1,0
       0     .04       0      40      .1       0     140     .12       0
     340      .1       0   444.9    .045       0   457.2      .1       0
#XS Ineff= 2 , 0
          345.76  3366.6
Permanent Ineff=
       F       F
Bank Sta=444.9,457.2
XS Rating Curve= 0 ,0
Exp/Cntr(USF)=0,0
Exp/Cntr=0.3,0.1

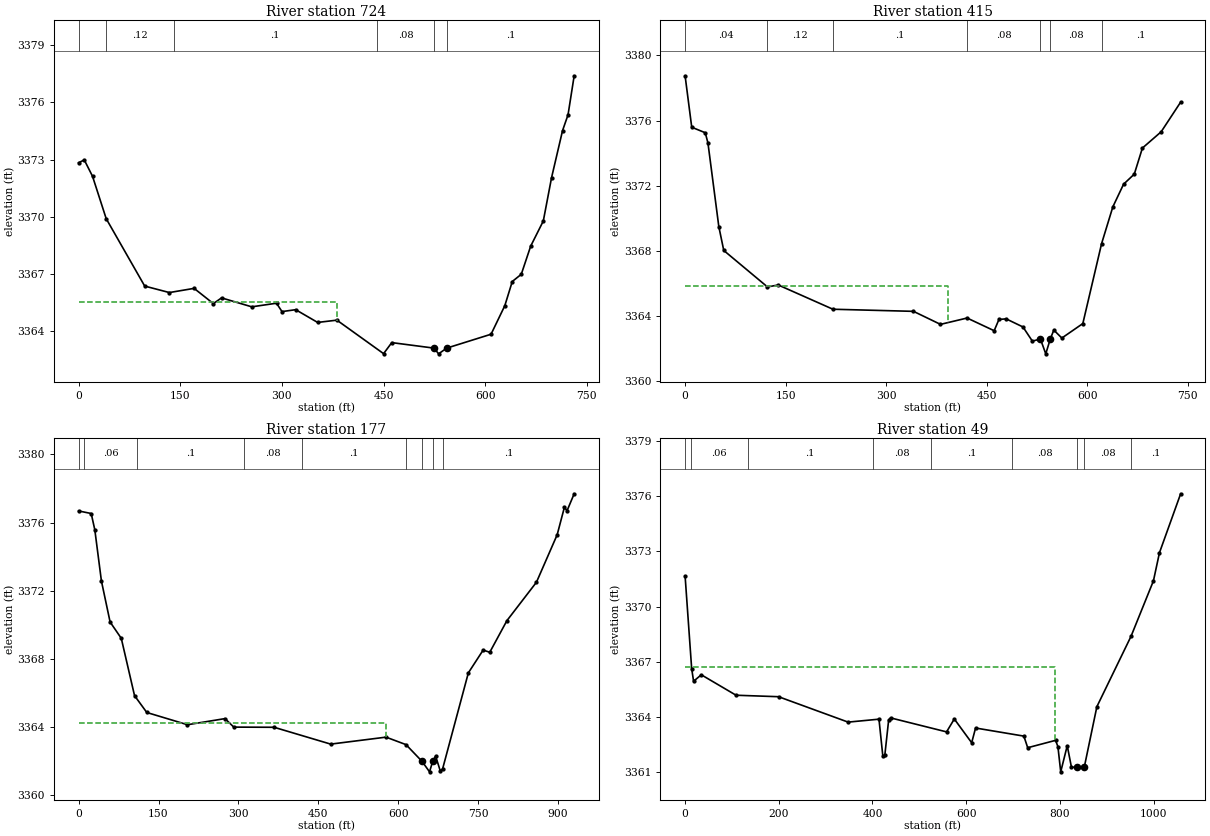
Type RM Length L Ch R = 1 ,724     ,241.3,308.4,228.5
XS GIS Cut Line= 4
 2180456.5450233436096.9537522912180376.67310461436592.159648171
2180360.69872087436672.0315668612180335.59611786436818.083075324
#Sta/Elev= 30
       0 3372.83     8.3 3372.98    20.5 3372.12    40.7 3369.89    97.5 3366.35
   133.9 3366.01   170.4 3366.23   198.8 3365.43   210.9 3365.73   255.5 3365.26
     292 3365.45   300.1 3365.01   320.3 3365.11   352.7 3364.44   381.1 3364.56
     450  3362.8   462.1 3363.38   524.5 3363.09   531.2 3362.79   543.1 3363.09
   608.6 3363.82   628.9 3365.32   639.9 3366.59   653.2 3366.97   667.1 3368.45
   685.7 3369.77   697.9 3372.05   714.1 3374.52   722.2 3375.35731.2526  3377.4
#Mann= 6 ,-1,0
       0     .04       0      40     .12       0     140      .1       0
     440     .08       0   524.5    .045       0   543.1      .1       0
#XS Ineff= 2 , 0
          381.96 3365.49
Permanent Ineff=
       F       F
Bank Sta=524.5,543.1
XS Rating Curve= 0 ,0
Exp/Cntr(USF)=0,0
Exp/Cntr=0.3,0.1

Type RM Length L Ch R = 1 ,415     ,232.2,238.1,192
XS GIS Cut Line= 4
2180212.36515759436019.3638884212180146.18556782 436516.85183912
2180146.18556782436585.3134837122180137.05734854436754.185540371
#Sta/Elev= 30
       0 3378.75     9.9 3375.59    30.1 3375.25    34.1 3374.62    50.3 3369.49
    57.7 3368.02   122.9 3365.78     139  3365.9   220.6 3364.41   340.8 3364.28
   381.1 3363.48   420.8 3363.87   461.2 3363.09   468.3 3363.78     479 3363.82
   504.2 3363.32   518.2 3362.45   530.2 3362.58   538.2 3361.67   544.93362.576
   550.2 3363.13   562.2 3362.64   593.5 3363.53   621.5 3368.44   638.3  3370.7
   654.3 3372.09   670.3 3372.71   682.4 3374.31   710.4 3375.31739.4507 3377.13
#Mann= 7 ,-1,0
       0     .04       0   122.9     .12       0   220.6      .1       0
   420.8     .08       0   530.2    .045       0   544.9     .08       0
   621.5      .1       0
#XS Ineff= 2 , 0
          392.68 3365.84
Permanent Ineff=
       F       F
Bank Sta=530.2,544.9
XS Rating Curve= 0 ,0
Exp/Cntr(USF)=0,0
Exp/Cntr=0.3,0.1

Type RM Length L Ch R = 1 ,177     ,145.5,128.5,118.4
XS GIS Cut Line= 4
 2180091.8180558435935.8480534432179931.61780746436529.410512052
2179970.64094488436625.9414309272180077.44111044436808.734021986
#Sta/Elev= 30
       0 3376.68    23.6 3376.53    30.4 3375.57    42.8 3372.56    59.1 3370.15
    80.1 3369.19     105 3365.82     128 3364.83   204.4 3364.11   274.9 3364.47
   291.4 3363.97   367.1 3363.96   473.4 3362.97   577.3 3363.38   614.8 3362.94
   644.8 3361.96     659 3361.34   665.13361.973   670.4 3362.27   679.3 3361.38
   683.6 3361.52   731.9 3367.16   759.7  3368.5   772.1 3368.37   804.3 3370.23
   859.8 3372.49   898.7 3375.28   912.3  3376.9   917.2 3376.69930.6274 3377.69
#Mann= 9 ,-1,0
       0     .04       0      10     .06       0     110      .1       0
     310     .08       0     420      .1       0   614.8     .08       0
   644.8    .045       0   665.1     .08       0   684.8      .1       0
#XS Ineff= 2 , 0
          576.34 3364.21
Permanent Ineff=
       F       F
Bank Sta=644.8,665.1
XS Rating Curve= 0 ,0
Exp/Cntr(USF)=0,0
Exp/Cntr=0.3,0.1

Type RM Length L Ch R = 1 ,49      ,,,
XS GIS Cut Line= 4
2180017.56214791435887.6099310212179829.12510485436641.550321317
2179910.60120384 436702.018667642180051.25990428436813.245176318
#Sta/Elev= 30
       0 3371.67      14 3366.64    18.1 3365.95    34.6  3366.3   108.8 3365.19
   199.5 3365.11     348 3363.73   413.9 3363.89   422.2 3361.87   426.3 3361.92
   434.6 3363.85   438.7 3363.96   558.2  3363.2   574.7  3363.9   611.8 3362.61
   620.1 3363.41   723.2 3362.97   731.4 3362.34   790.9 3362.74   795.9  3362.4
   801.9 3361.03   815.8 3362.45   824.8 3361.28   836.9 3361.28  852.15 3361.28
   879.1 3364.57     952 3368.39   999.8  3371.4  1012.7 3372.93  1057.9 3376.13
#Mann= 9 ,-1,0
       0     .04       0    12.4     .06       0   133.4      .1       0
   401.1     .08       0   524.6      .1       0   697.6     .08       0
   836.9    .045       0  852.15     .08       0     952      .1       0
#XS Ineff= 2 , 0
          788.94 3366.75
Permanent Ineff=
       F       F
Bank Sta=836.9,852.15
XS Rating Curve= 0 ,0
Exp/Cntr(USF)=0,0
Exp/Cntr=0.3,0.1
LCMann Table=0

Chan Stop Cuts=-1
Use User Specified Reach Order=0
Composite Channel Slope=5